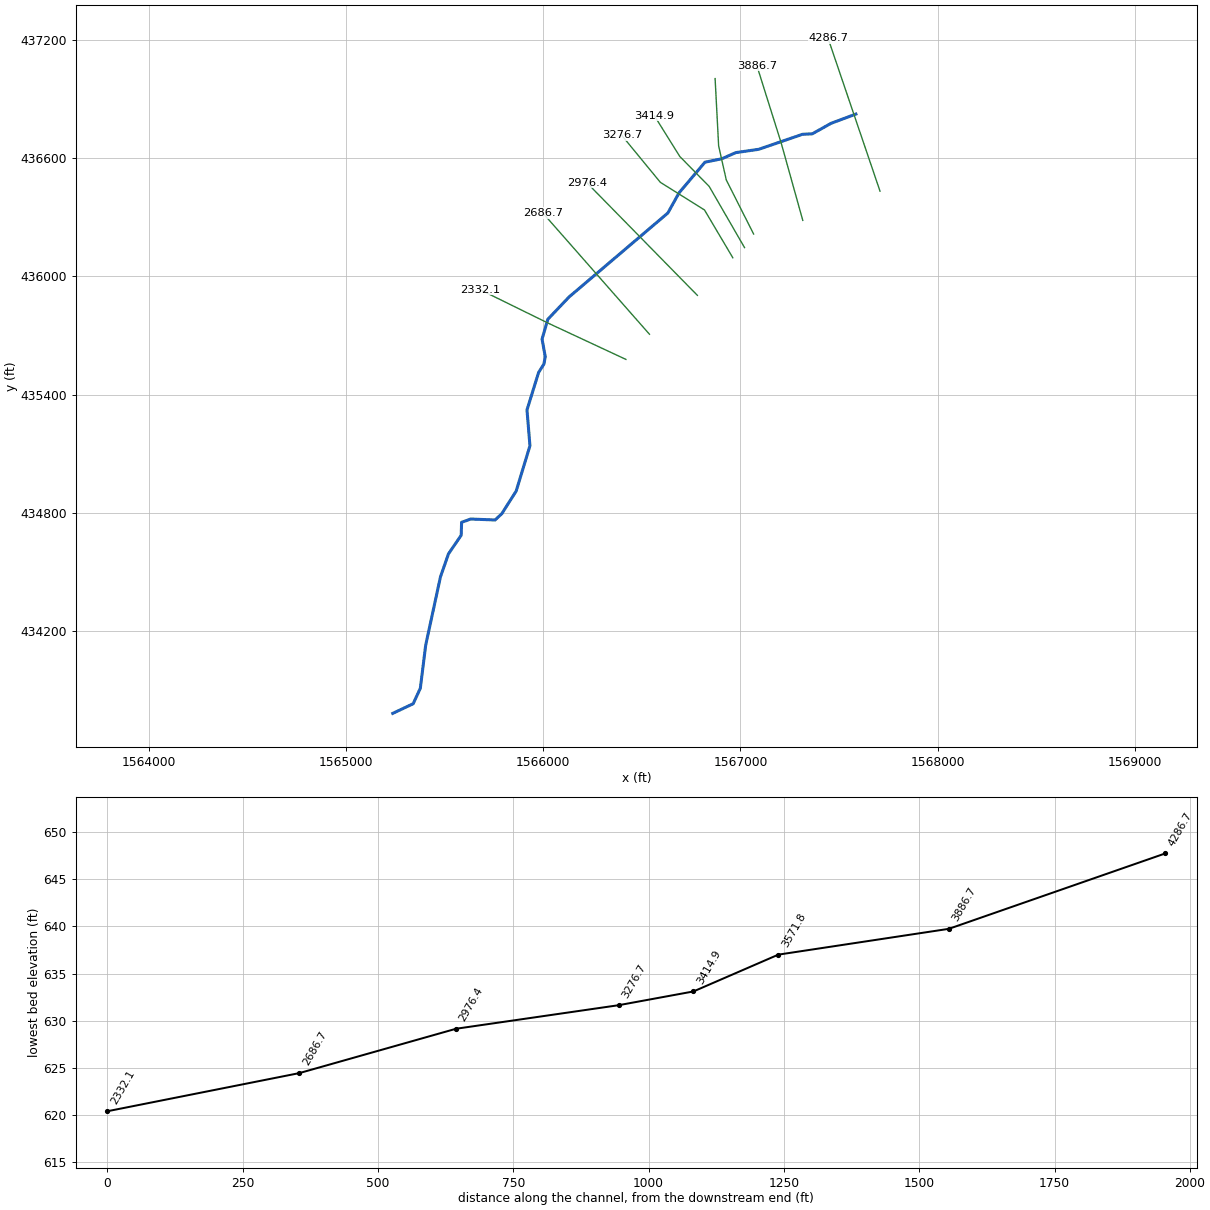
--- NEWCOMBCR2.prj (project) ---

Proj Title=NEWCOMBCR2
Current Plan=p01
Default Exp/Contr=0,0
English Units
Geom File=g01
Flow File=f01
Plan File=p01
BEGIN DESCRIPTION:
END DESCRIPTION:
DSS Export Rating Curves= 0
DSS Export Rating Curve Sorted= 0
DSS Export Volume Flow Curves= 0
DXF OffsetX= 0
DXF OffsetY= 0
DXF ScaleX= 0
DXF ScaleY= 0

--- NEWCOMBCR2.p01 (plan) ---

Plan Title=Floodplain
Program Version=4.00
Geom File=g01
Flow File=f01
K Sum by GR=0
Std Step Tol=0.01
Critical Tol=0.01
Num of Std Step Trials=20
Max Error Tol=0.3
Flow Tol Ratio=0.001
Split Flow NTrial=30
Split Flow Tol=0.02
Split Flow Ratio=0.02
Log Output Level=0
Friction Slope Method=1
Unsteady Friction Slope Method=2
Unsteady Bridges Friction Slope Method=1
Global Log Level=0
CheckData=False
Run HTab=0
Run UNet=0
Run PostProcess=0
UNET Theta=0
UNET Theta Warmup=0
UNET ZTol=0
UNET ZSATol=0
UNET MxIter=0
UNET MaxInSteps=0
UNET DtIC=0
UNET DtMin=0
UNET MaxCRTS=0
UNET WFStab=0
UNET SFStab=0
UNET WFX=0
UNET SFX=0
UNET DSS MLevel=0
UNET DZMax Abort=0
UNET Convert EG Bridges=0
UNET Use Existing IB Tables=0
UNET Froude Limit=0
UNET Froude Power=0
Write IC File=0
Echo Input=False
Echo Output=False
Write Detailed=0

--- NEWCOMBCR2.f01 (steady flow) ---

Flow Title=NFF Regression Equation
Program Version=4.00
Number of Profiles=1
Profile Names=P100yr
River Rch & RM=NEWCOMBCR2,Main      ,4286.7
     355
River Rch & RM=NEWCOMBCR2,Main      ,3571.8
     374
River Rch & RM=NEWCOMBCR2,Main      ,3276.7
     561
Boundary for River Rch & Prof#=NEWCOMBCR2,Main      ,1
Up Type=0
Dn Type=3
Dn Slope=0.012005

--- NEWCOMBCR2.g01 (geometry) ---

Geom Title=USGS 10m DEM
Program Version=4.00

River Reach=NEWCOMBCR2      ,Main
Reach XY= 30
     1567585.265      436823.886     1567459.525      436777.121
     1567364.185      436723.733     1567314.567      436721.305
     1567092.305      436645.104     1566975.928      436628.238
     1566906.222      436597.359     1566820.047      436579.854
     1566688.764      436424.565     1566631.511      436321.702
     1566129.726      435894.713     1566022.885      435782.161
      1565993.66      435681.684     1566009.988      435591.935
     1566002.819      435554.375     1565976.165      435512.469
       1565917.2      435322.085      1565932.23      435140.107
     1565862.403      434910.265     1565789.443      434795.248
     1565755.377      434763.467     1565631.384      434768.235
     1565585.596      434751.585     1565583.515      434686.024
     1565518.995      434591.325      1565478.41      434474.773
     1565403.483      434128.238     1565376.223      433909.047
     1565340.004      433830.614     1565236.425      433781.699

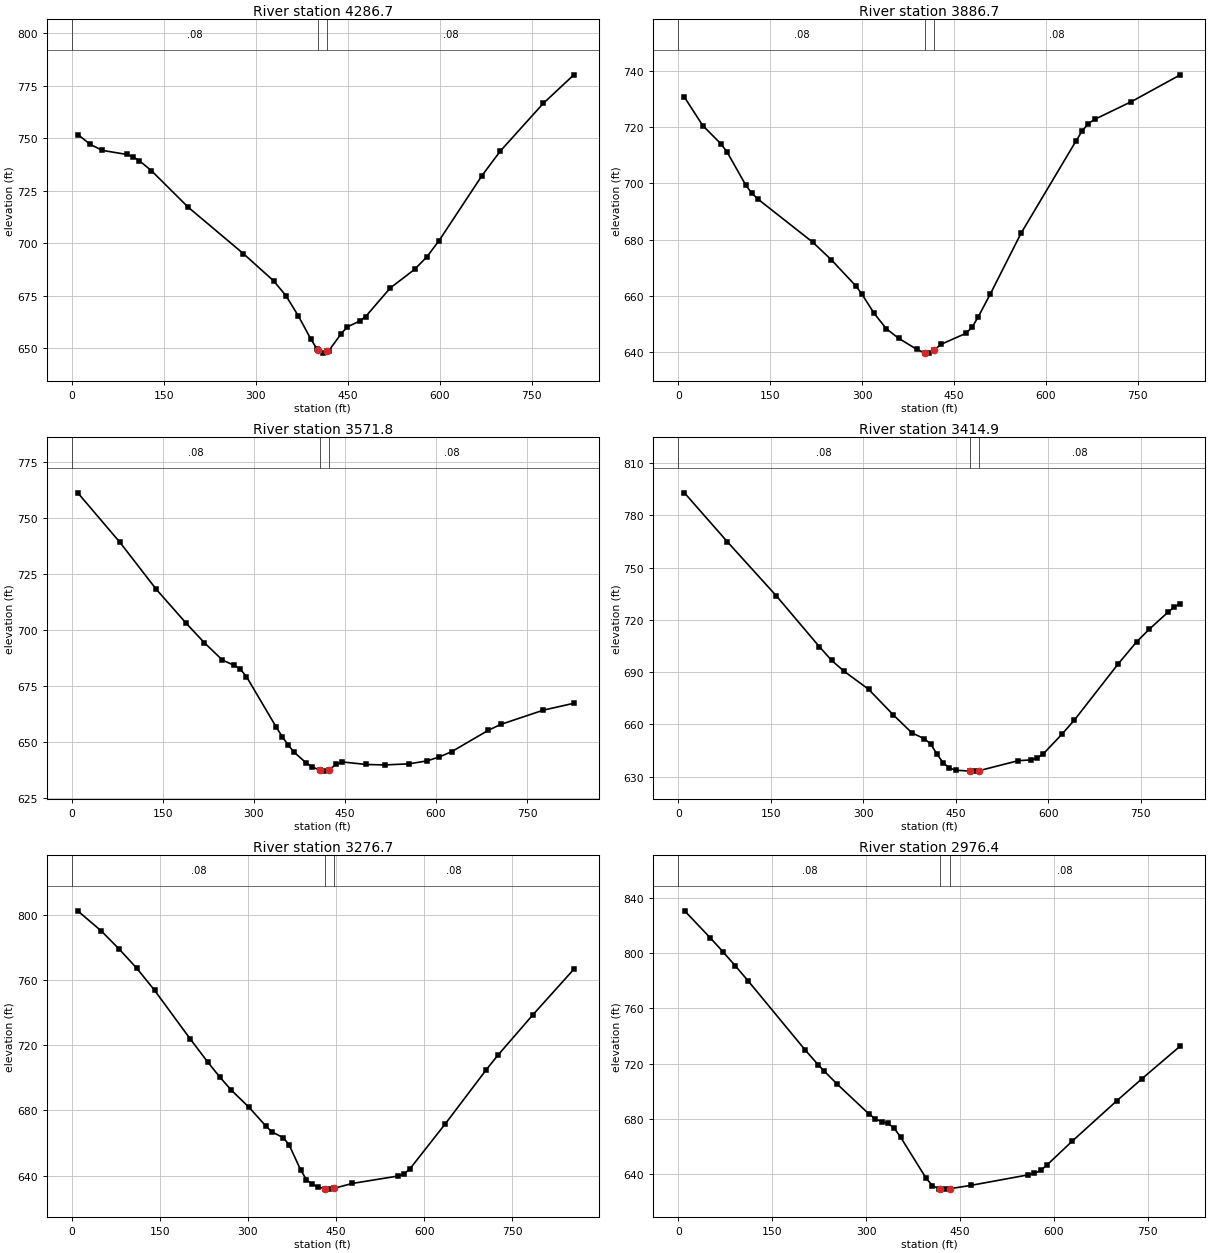
Type RM Length L Ch R = 1 ,4286.7  ,401.3,400,399.4
XS GIS Cut Line= 3
     1567707.436      436432.908     1567575.795      436820.672
     1567444.154      437208.436
#Sta/Elev= 30
      10   751.8      30  747.16    49.9  744.26    89.9  742.32    99.9  741.18
   109.9  739.41   129.8  734.64   189.8  717.24   279.7  695.17   329.6  682.07
   349.6  674.99   369.5  665.52   389.5  654.72   399.5  649.93     402  649.38
   409.5  647.76     417  648.68   419.5  648.99   439.5     657   449.5  660.25
   469.4  662.97   479.4  665.17   519.4  678.73   559.3  687.64   579.3   693.6
   599.3  701.37   669.2  732.29   699.1  743.96   769.1  766.62     819  780.23
#Mann= 3 , 0 , 0
       0     .08       0     402    .045       0     417     .08       0
Bank Sta=402,417
XS Rating Curve= 0 ,0
Exp/Cntr=0.3,0.1

Type RM Length L Ch R = 1 ,3886.7  ,316.1,315,313
XS GIS Cut Line= 3
     1567315.885      436284.312     1567205.932      436678.726
     1567083.076       437069.64
#Sta/Elev= 30
      10  730.68    39.9  720.56    69.9  714.01    79.9  711.08   109.9   699.5
   119.8  696.58   129.8  694.48   219.7  679.09   249.7  672.91   289.6  663.66
   299.6  660.73   319.6  653.88   339.5  648.42   359.5  645.03   389.5  641.06
     402  639.83   409.5  639.75     417   640.8   429.4  642.93   469.4  646.78
   479.4  648.93   489.4   652.6   509.4  660.83   559.4  682.33   649.3  715.18
   659.3   718.7   669.3  721.27   679.3  722.73   739.3  729.03   819.2  738.56
#Mann= 3 , 0 , 0
       0     .08       0     402    .045       0     417     .08       0
Bank Sta=402,417
XS Rating Curve= 0 ,0
Exp/Cntr=0.3,0.1

Type RM Length L Ch R = 1 ,3571.8  ,143.7,156.9,170.1
XS GIS Cut Line= 4
      1567066.59      436214.896     1566927.946      436489.433
     1566889.131      436662.605     1566871.256      437004.069
#Sta/Elev= 30
     9.9  761.41    79.4  739.25   138.9  718.38   188.5  703.09   218.3  694.43
     248  686.69   267.9  684.23   277.8  682.52   287.7  679.26   337.1  656.54
     347  652.31   356.9  648.51   366.7  645.35   386.4   640.6   396.3  638.89
   408.5  637.44     416  637.01   423.5  637.69   435.7  639.99   445.6  641.12
     485  639.98   515.2  639.78   555.4  640.26   585.6  641.61   605.7  643.38
   625.8  645.72   686.2  655.27   706.3  657.86   776.7  664.26     827  667.34
#Mann= 3 , 0 , 0
       0     .08       0   408.5    .045       0   423.5     .08       0
Bank Sta=408.5,423.5
XS Rating Curve= 0 ,0
Exp/Cntr=0.3,0.1

Type RM Length L Ch R = 1 ,3414.9  ,132.9,138.2,143.5
XS GIS Cut Line= 4
     1567020.504      436146.072     1566841.359      436456.589
     1566692.072      436608.862     1566563.685      436814.878
#Sta/Elev= 30
      10  792.91    79.7   764.8   159.3  733.68     229  704.53   248.9  696.68
   268.9  690.48   308.7  680.13   348.5  665.53   378.8  655.15   399.1  651.69
   409.3  648.79   419.4  643.06   429.6  637.98   439.7  634.91   449.9  633.64
   472.8  633.12   480.3   633.1   487.8  633.33   551.4  639.09   571.7  639.54
   581.8  640.52     592  642.92   622.3  654.23   642.5  662.36   713.3   694.5
   743.7  707.37   763.9  714.51   794.3  724.29   804.4  727.31   814.5  729.25
#Mann= 3 , 0 , 0
       0     .08       0   472.8    .045       0   487.8     .08       0
Bank Sta=472.8,487.8
XS Rating Curve= 0 ,0
Exp/Cntr=0.3,0.1

Type RM Length L Ch R = 1 ,3276.7  ,305.6,300.3,295
XS GIS Cut Line= 4
     1566961.093      436094.476     1566817.473       436337.16
     1566593.543      436477.489     1566397.749      436716.004
#Sta/Elev= 30
    10.1  802.76    50.4  790.33    80.6  779.27   110.8  767.39     141  753.89
   201.4  724.11   231.6  709.74   251.8  700.64   271.9   692.4   301.6  682.02
   330.9  670.26   340.7  666.87   360.3  663.22   370.1   658.8   389.7  643.43
   399.4  637.52   409.2  634.69     419  633.08   431.1  631.86   438.6  631.64
   446.1   632.1   477.7  635.14   556.2  639.73   566.2  641.06   576.1  644.29
   635.9  671.77   705.5  704.95   725.4  713.95   785.2  738.87   854.8  766.84
#Mann= 3 , 0 , 0
       0     .08       0   431.1    .045       0   446.1     .08       0
Bank Sta=431.1,446.1
XS Rating Curve= 0 ,0
Exp/Cntr=0.3,0.1

Type RM Length L Ch R = 1 ,2976.4  ,290.9,289.6,288.4
XS GIS Cut Line= 2
      1566781.42      435903.574     1566219.942      436476.281
#Sta/Elev= 30
    10.2  830.63    50.8  811.23    71.1  801.17    91.4  790.68   111.7  779.89
     203  729.74   223.3  719.31   233.5  714.42   253.8  705.21   304.6  683.57
   314.7  680.03   324.9  677.94     335   676.8   345.2   673.2   355.3  666.68
   395.9  637.06   406.1  631.67   416.2  629.31   418.9  629.27   426.4  629.14
   433.9  629.44     467  631.82   558.4  639.41   568.5  640.48   578.7  642.65
   588.8   646.5   629.4   663.9   700.5  693.08   741.1   709.2     802  732.74
#Mann= 3 , 0 , 0
       0     .08       0   418.9    .045       0   433.9     .08       0
Bank Sta=418.9,433.9
XS Rating Curve= 0 ,0
Exp/Cntr=0.3,0.1

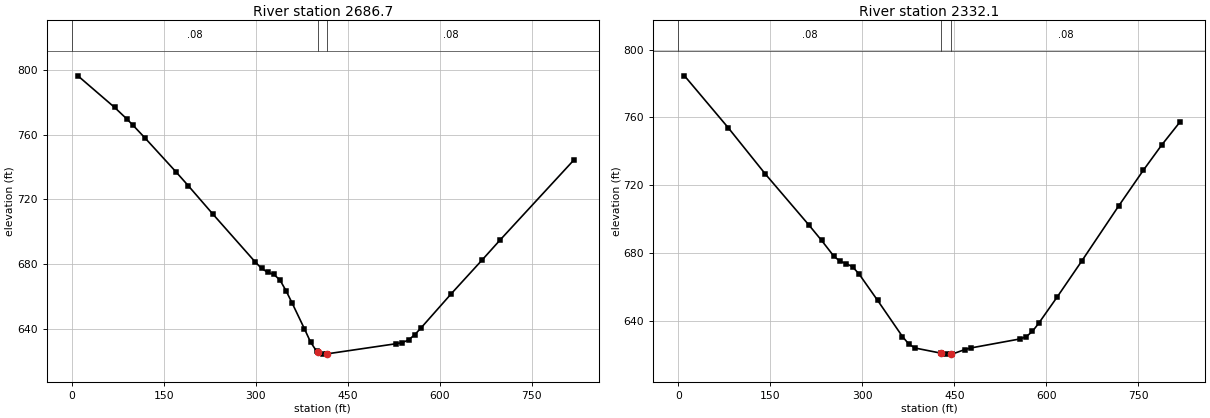
Type RM Length L Ch R = 1 ,2686.7  ,345.4,354.6,363.5
XS GIS Cut Line= 3
     1566538.361      435706.233     1566268.111      436013.893
      1565997.86      436321.553
#Sta/Elev= 30
      10  796.39    69.9  776.86    89.9   769.7    99.9  765.85   119.9   757.8
   169.8  737.13   189.8  728.59   229.7  711.15   299.6  681.22   309.6  677.39
   319.6  674.97   329.6  673.69   339.6  670.22   349.6  663.54   359.6  655.87
   379.5   640.1   389.5   631.9   399.5  626.14     402  625.71   409.5  624.43
     417  624.63   529.4  630.88   539.3  631.57   549.3  633.18   559.3  636.36
   569.3  640.45   619.2  661.82   669.2  682.53   699.1  695.12     819  744.37
#Mann= 3 , 0 , 0
       0     .08       0     402    .045       0     417     .08       0
Bank Sta=402,417
XS Rating Curve= 0 ,0
Exp/Cntr=0.3,0.1

Type RM Length L Ch R = 1 ,2332.1  ,2340.3,2332.1,2321.8
XS GIS Cut Line= 3
      1566418.94      435578.521     1566023.425      435763.204
     1565680.924      435931.648
#Sta/Elev= 30
    10.2  784.54    81.2  754.03   142.1  726.55   213.2  696.42   233.5   687.5
   253.8  678.05   263.9  675.12   274.1  673.74   284.2  671.82   294.4  667.78
   324.8  652.14   365.4  630.74   375.6  626.37   385.8  623.99     429  620.89
   436.5  620.38     444  620.41   446.6  620.42   466.6  623.03   476.7  624.01
     557  629.34   567.1  630.66   577.1  633.77   587.2  638.46   617.3  653.96
   657.5  675.25   717.7  707.75   757.9  728.82   788.1  743.84   818.2  757.56
#Mann= 3 , 0 , 0
       0     .08       0     429    .045       0     444     .08       0
Bank Sta=429,444
XS Rating Curve= 0 ,0
Exp/Cntr=0.3,0.1

Chan Stop Cuts=-1
Use User Specified Reach Order=0